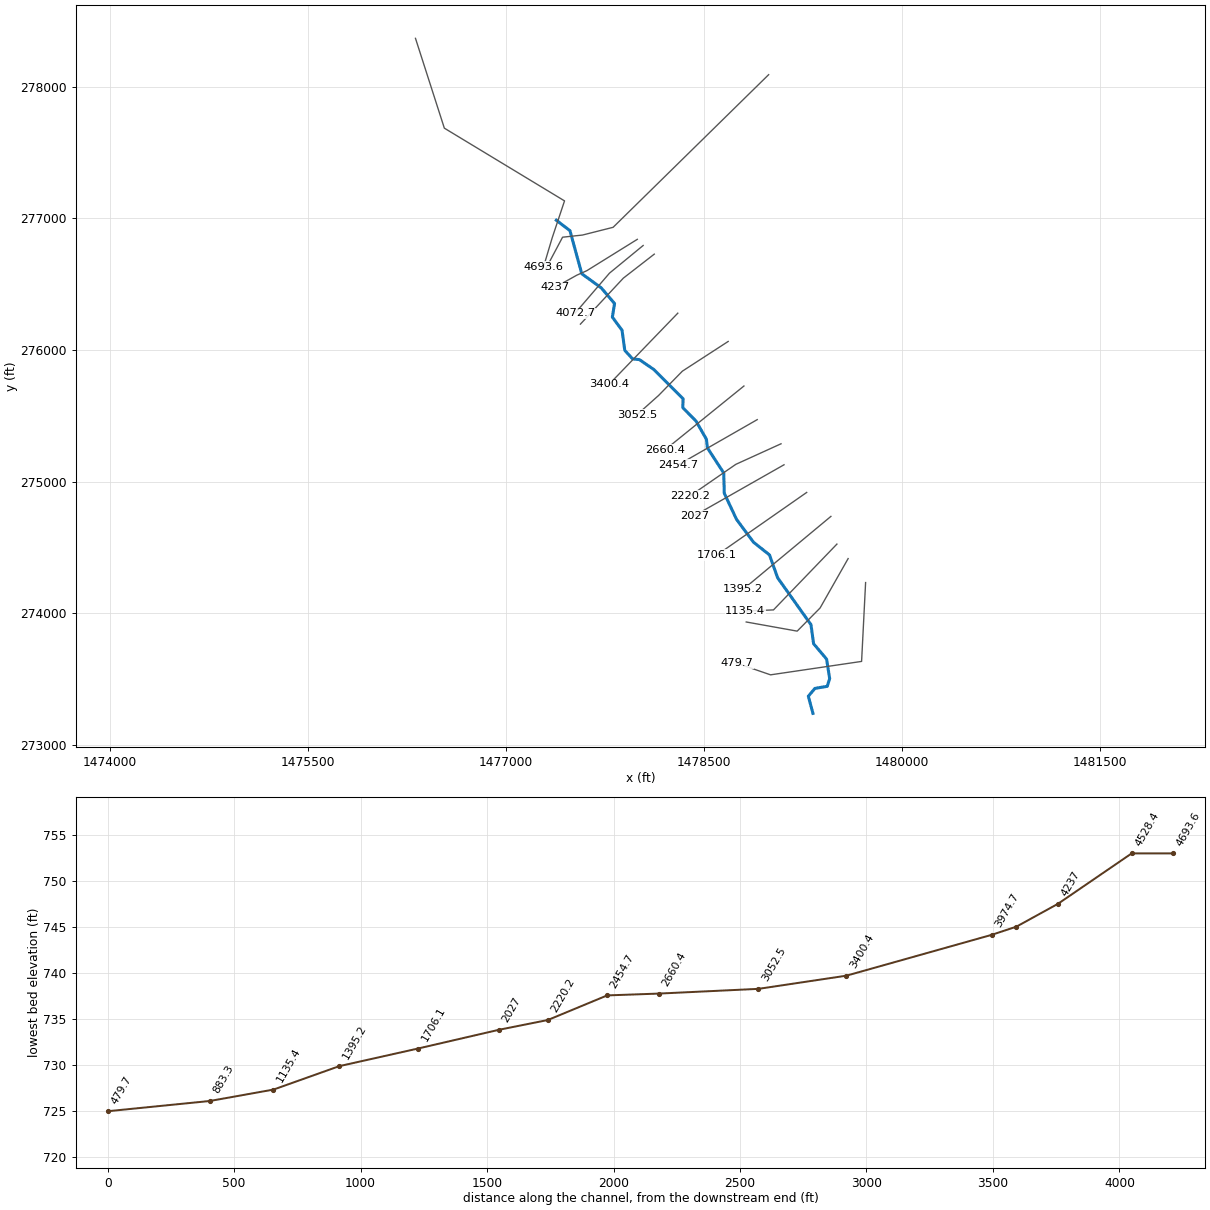
--- ELLIOTSRN.prj (project) ---

Proj Title=ELLIOTSRN
Current Plan=p01
Default Exp/Contr=0,0
English Units
Geom File=g01
Flow File=f01
Plan File=p01
BEGIN DESCRIPTION:
END DESCRIPTION:
DSS Export Rating Curves= 0
DSS Export Rating Curve Sorted= 0
DSS Export Volume Flow Curves= 0
DXF OffsetX= 0
DXF OffsetY= 0
DXF ScaleX= 0
DXF ScaleY= 0

--- ELLIOTSRN.p01 (plan) ---

Plan Title=Floodplain
Program Version=4.00
Geom File=g01
Flow File=f01
K Sum by GR=0
Std Step Tol=0.01
Critical Tol=0.01
Num of Std Step Trials=20
Max Error Tol=0.3
Flow Tol Ratio=0.001
Split Flow NTrial=30
Split Flow Tol=0.02
Split Flow Ratio=0.02
Log Output Level=0
Friction Slope Method=1
Unsteady Friction Slope Method=2
Unsteady Bridges Friction Slope Method=1
Global Log Level=0
CheckData=False
Run HTab=0
Run UNet=0
Run PostProcess=0
UNET Theta=0
UNET Theta Warmup=0
UNET ZTol=0
UNET ZSATol=0
UNET MxIter=0
UNET MaxInSteps=0
UNET DtIC=0
UNET DtMin=0
UNET MaxCRTS=0
UNET WFStab=0
UNET SFStab=0
UNET WFX=0
UNET SFX=0
UNET DSS MLevel=0
UNET DZMax Abort=0
UNET Convert EG Bridges=0
UNET Use Existing IB Tables=0
UNET Froude Limit=0
UNET Froude Power=0
Write IC File=0
Echo Input=False
Echo Output=False
Write Detailed=0

--- ELLIOTSRN.f01 (steady flow) ---

Flow Title=NFF Regression Equation
Program Version=4.10
Number of Profiles= 1
Profile Names=P100yr
River Rch & RM=ELLIOTSRN,Main            ,4693.6
883.3799
River Rch & RM=ELLIOTSRN,Main            ,4237
1176.878
River Rch & RM=ELLIOTSRN,Main            ,883.3
1237.572
River Rch & RM=ELLIOTSRN,Main            ,479.7
1238.777
Boundary for River Rch & Prof#=ELLIOTSRN,Main            , 1
Up Type= 0
Dn Type= 3
Dn Slope=0.0025
DSS Import GetInterval= 0
DSS Import GetPeak= 0
DSS Import FillOption= 0

--- ELLIOTSRN.g01 (geometry) ---

Geom Title=USGS 10m DEM
Program Version=4.10

River Reach=ELLIOTSRN       ,Main
Reach XY= 30
     1477382.178      276985.363     1477485.581      276905.687
     1477575.048      276578.765     1477722.884      276471.239
     1477823.494      276352.412     1477806.878      276249.202
     1477880.229      276149.376     1477901.002      275996.515
     1477959.988       275932.37     1478012.482      275926.106
     1478123.128      275849.835     1478343.202      275628.791
     1478340.771      275561.777     1478441.118      275459.347
     1478519.938        275321.5     1478527.577      275255.527
     1478651.188      275064.902     1478655.354      274910.736
     1478748.424      274712.457     1478876.549       274539.54
     1478997.903      274443.186     1479059.883      274268.707
     1479312.487      273912.978     1479332.278      273768.186
     1479430.716       273651.52     1479454.153      273504.124
     1479435.823       273444.67     1479342.594      273429.045
     1479292.381      273369.554       1479327.4      273239.178

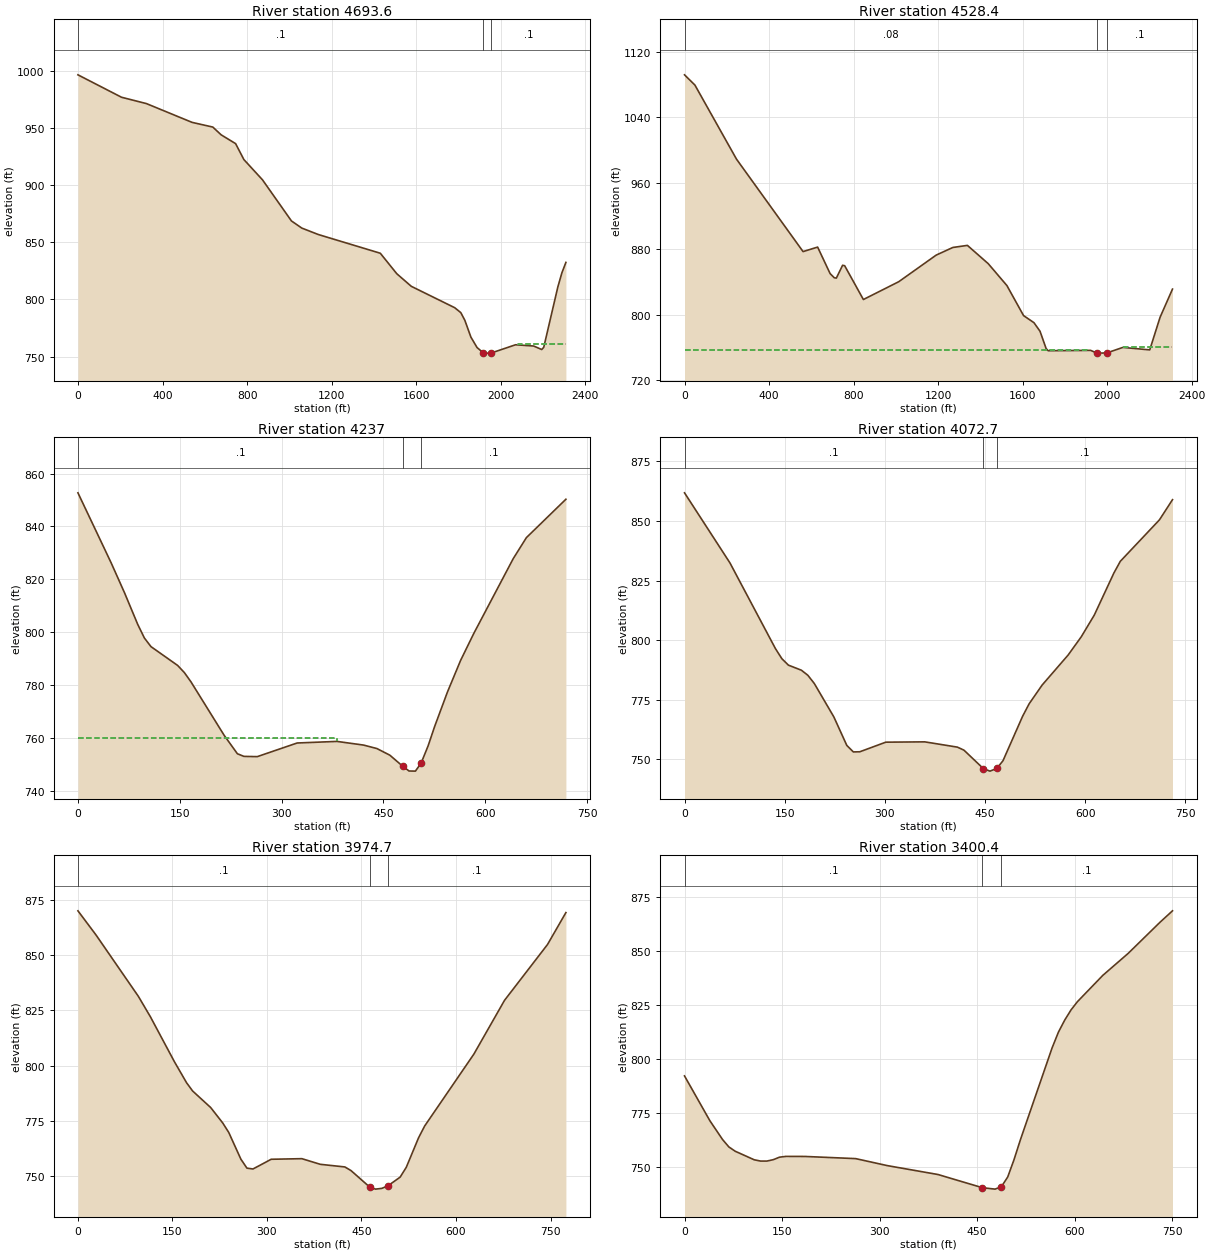
Type RM Length L Ch R = 1 ,4693.6  ,194.1,165.2,135.9
XS GIS Cut Line= 5
     1476314.466      278366.989     1476533.216      277684.697
     1477444.306      277132.158     1477350.274      276850.062
     1477285.169      276630.877
#Sta/Elev= 30
       0  996.75   206.1  977.11   323.9  971.56   539.8  955.11     638  950.99
   677.2  944.21   745.8  936.48   784.9  922.53   872.9  904.79  1009.8  868.79
  1058.6  862.54  1136.8  856.89  1430.1  840.49  1508.3   822.5  1576.8   811.5
    1782  792.79  1810.8  788.48    1830  781.74  1858.8  766.97  1887.6  757.94
  1916.3   753.4  1935.5     753 1955.25753.1288  2069.8  760.32  2155.6  759.22
  2193.7  756.15  2203.2  758.12  2269.9  810.98    2289  823.34    2308  832.47
#Mann= 3 , 0 , 0
       0      .1       0  1916.3    .045       0 1955.25      .1       0
#XS Ineff= 2 , 0
                         2079.76          760.69
Permanent Ineff=
       F       F
Bank Sta=1916.3,1955.25
XS Rating Curve= 0 ,0
Exp/Cntr=0.3,0.1

Type RM Length L Ch R = 1 ,4528.4  ,283.5,291.3,299.4
XS GIS Cut Line= 5
      1478991.55      278090.947     1477812.654      276931.524
     1477580.308      276872.631     1477429.484      276856.355
     1477305.786      276623.065
#Sta/Elev= 30
       0 1091.92    49.2 1079.45   246.1   989.2     561  876.65   629.9  882.14
     689  849.83   708.6  844.78   718.5  844.36     748  859.99   757.8  859.46
   846.4  818.28  1013.8  839.99  1190.9  872.38  1269.6  881.66  1338.6  884.21
    1437  861.98  1525.6  835.26  1604.3  798.72  1653.5  790.07  1682.3  779.62
    1711  758.62  1720.6  755.92  1921.6  756.36  1950.1  753.16  1959.6     753
  1997.5  753.18  2074.2  759.95  2201.4  756.96  2250.3  796.68    2309  830.96
#Mann= 3 , 0 , 0
       0     .08       0  1950.1    .045       0  1997.5      .1       0
#XS Ineff= 2 , 0
         1912.16  757.32 2073.97          760.12
Permanent Ineff=
       F       F
Bank Sta=1950.1,1997.5
XS Rating Curve= 0 ,0
Exp/Cntr=0.3,0.1

Type RM Length L Ch R = 1 ,4237    ,153.2,164.3,175.4
XS GIS Cut Line= 4
      1477995.89      276840.079     1477613.728      276602.203
     1477536.689       276567.48     1477376.098       276477.42
#Sta/Elev= 30
       0   852.7    48.9  826.25    68.5     815    88.1  802.97    97.9  797.83
   107.6  794.58   146.8  787.48   156.6  784.82   166.4  781.31   215.3   761.1
   234.9  754.09   244.6   753.1   264.2  753.01   322.9  758.16   381.6  758.76
   420.8  757.37   440.4  756.06   459.5  753.55   478.3   749.4   487.7  747.58
   497.1  747.53   505.5750.5429   515.9  757.13   525.3   764.3   544.3  777.42
   563.7  789.38   583.1  799.56   641.2  827.83   660.6  835.77   718.8  850.28
#Mann= 3 , 0 , 0
       0      .1       0   478.3    .045       0   505.5      .1       0
#XS Ineff= 2 , 0
          381.93  760.16
Permanent Ineff=
       F       F
Bank Sta=478.3,505.5
XS Rating Curve= 0 ,0
Exp/Cntr=0.3,0.1

Type RM Length L Ch R = 1 ,4072.7  ,98.9,98,96.8
XS GIS Cut Line= 3
     1478040.378      276793.392     1477785.169      276583.323
     1477524.753      276279.503
#Sta/Elev= 30
       0  861.83      68  832.44   136.1  796.49   145.8  792.22   155.6  789.52
     175   787.4   184.7  785.27   194.4   781.8   223.6  767.81     243  755.85
   252.8  753.11   262.5  753.17   301.4   757.2   359.8  757.33   408.6  755.12
   418.4  753.86   447.7  746.06   457.4  745.05   467.7746.1763   476.9  749.42
   506.2  768.02     516  773.28   535.5  781.16   574.5  793.79   594.1  801.42
   613.6  810.52   642.9  828.15   652.6   833.1   711.2   850.5   730.7  858.95
#Mann= 3 , 0 , 0
       0      .1       0   447.7    .045       0   467.7      .1       0
Bank Sta=447.7,467.7
XS Rating Curve= 0 ,0
Exp/Cntr=0.3,0.1

Type RM Length L Ch R = 1 ,3974.7  ,575.5,574.2,571.8
XS GIS Cut Line= 3
     1478124.579      276727.666     1477890.204      276545.374
     1477564.683      276195.982
#Sta/Elev= 30
       0  869.99    28.7  859.07    95.8  831.37   114.9  822.14   153.2  801.72
   172.4  792.26     182  788.53   210.7  781.04   229.9  774.03   239.4  769.76
   258.6   757.7   268.2  753.65   277.8  753.27   306.7  757.66   355.4  757.93
   384.6  755.38   423.6  754.19   433.4  752.54   462.8745.1493   472.3  744.16
   482.1  744.49   491.8  745.62   511.3  749.58   521.1  754.04   540.6  767.39
   550.3  772.73   628.3  805.19     677  829.53   745.2  854.76   774.4   869.2
#Mann= 3 , 0 , 0
       0      .1       0   462.8    .045       0   491.8      .1       0
Bank Sta=462.8,491.8
XS Rating Curve= 0 ,0
Exp/Cntr=0.3,0.1

Type RM Length L Ch R = 1 ,3400.4  ,345,347.9,347.4
XS GIS Cut Line= 2
     1478302.965      276279.315     1477782.131       275738.95
#Sta/Elev= 30
       0  792.12      39  771.39    58.5  762.69    68.2  759.26      78  757.26
   107.2  753.31     117  752.71   126.7  752.71   136.5  753.36   146.2  754.52
     156  754.88   185.2  754.85   263.2  753.85   311.9  750.61   389.9  746.49
   458.1  740.39   477.6  739.73   487.3  740.81   497.1  745.36   506.8  753.38
   516.6  762.58   565.3  805.06   575.1  812.39   584.8  817.98   594.6  822.73
   604.3  826.47   643.3  838.64   682.3  848.81     731  863.14   750.5  868.52
#Mann= 3 , 0 , 0
       0      .1       0   458.1    .045       0   487.3      .1       0
Bank Sta=458.1,487.3
XS Rating Curve= 0 ,0
Exp/Cntr=0.3,0.1

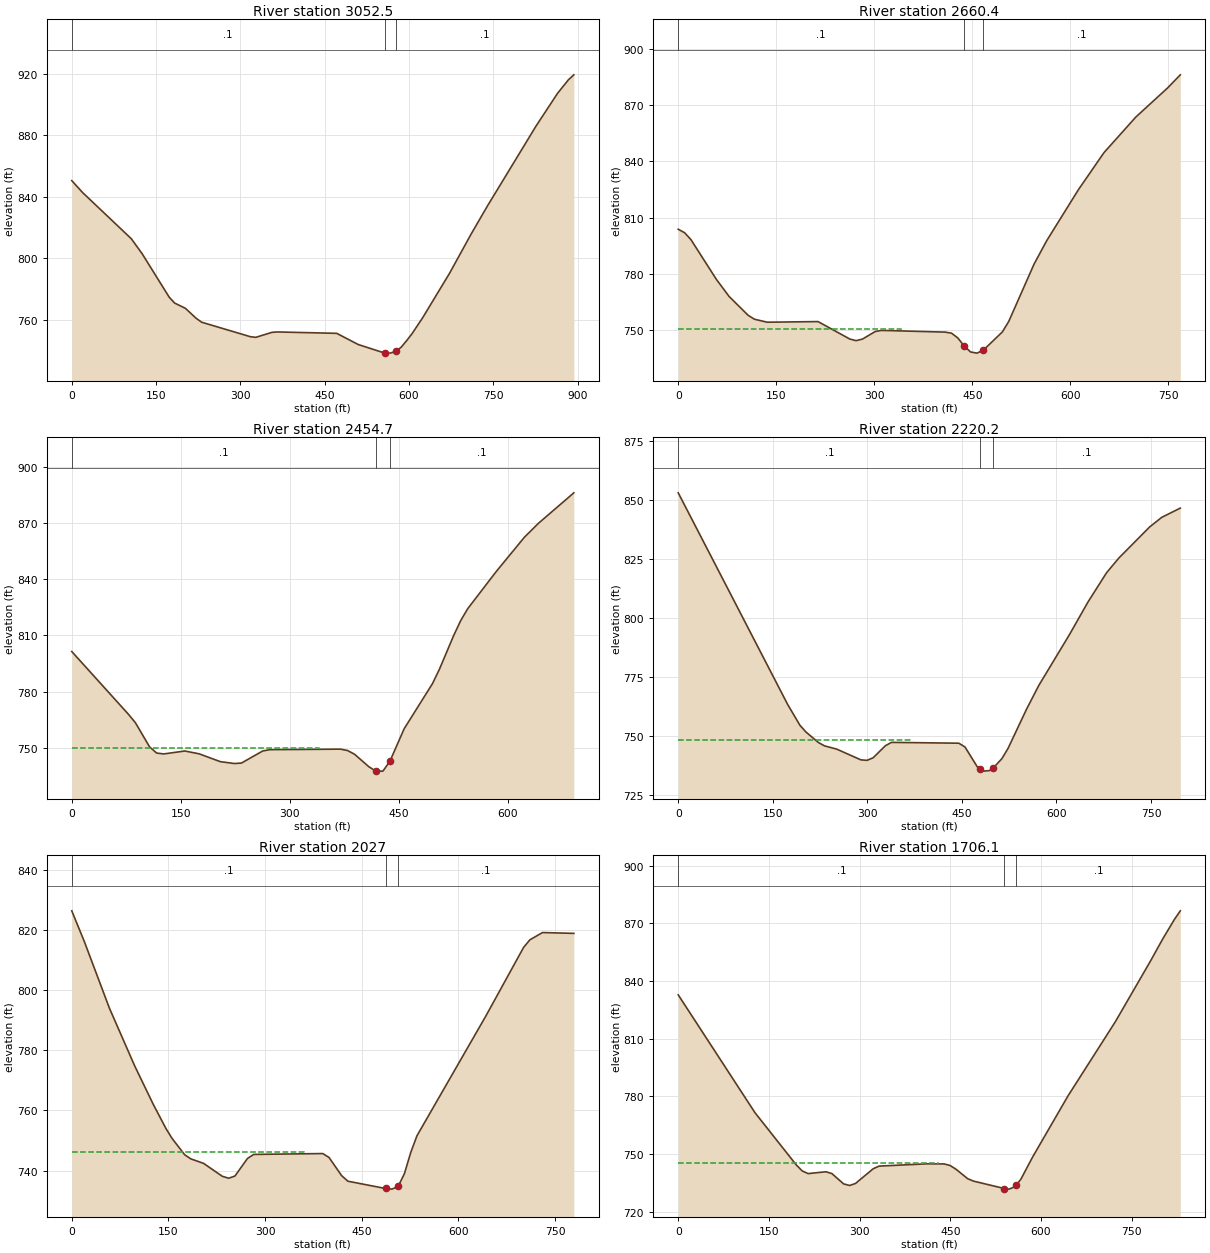
Type RM Length L Ch R = 1 ,3052.5  ,395.3,392.1,386.2
XS GIS Cut Line= 4
     1478684.909      276064.471     1478337.687      275838.777
     1478157.565      275654.315     1477992.635      275506.746
#Sta/Elev= 30
       0  850.48    19.3  842.72   105.9  812.71   125.2  802.96   173.4  774.67
     183  770.86   202.2  767.44   221.5   760.9   231.1  758.41   317.8  748.98
   327.4  748.57   356.3  751.83     366  752.07   471.4  751.17   509.6  743.91
   556.6  738.36   557.4   738.3   566.9  738.35   576.6739.4089     586  742.13
   595.6  746.31   605.1  750.77   624.2  761.24   671.9  790.07   710.4  815.63
   739.3  833.84   825.9  885.89   864.4   907.3   883.6  916.03   893.3  919.29
#Mann= 3 , 0 , 0
       0      .1       0   556.6    .045       0   576.6      .1       0
Bank Sta=556.6,576.6
XS Rating Curve= 0 ,0
Exp/Cntr=0.3,0.1

Type RM Length L Ch R = 1 ,2660.4  ,208.5,205.7,201.6
XS GIS Cut Line= 2
     1478804.267       275725.93     1478207.478      275241.989
#Sta/Elev= 30
       0  803.86     9.7  802.02    19.4  798.36    58.4  777.12    77.8  768.04
     107  757.96   116.7  755.87   136.2  754.28     214  754.61   262.6   745.3
   272.3  744.44     282  745.29   301.5  749.32   311.2  749.91   408.5     749
   418.2  748.44   427.9  745.87   437.7  741.58   447.4  738.41   457.1  737.79
   466.8  739.31     496  749.08   505.8  754.66   544.6  785.28   564.1  797.86
   612.7  825.09   651.6  844.73   700.3   863.7   748.9  879.21   768.4  886.22
#Mann= 3 , 0 , 0
       0      .1       0   437.7    .045       0   466.8      .1       0
#XS Ineff= 2 , 0
          340.42  750.51
Permanent Ineff=
       F       F
Bank Sta=437.7,466.8
XS Rating Curve= 0 ,0
Exp/Cntr=0.3,0.1

Type RM Length L Ch R = 1 ,2454.7  ,229.1,234.5,236.8
XS GIS Cut Line= 2
     1478904.961      275470.475     1478306.003      275126.725
#Sta/Elev= 30
       0  801.39    77.8  767.99    87.5  763.44     107  750.55   116.7  747.24
   126.4  746.76   155.6  748.32   175.1  746.83   204.3  742.65   223.7  741.65
   233.4  741.89   262.6  748.33   272.4  749.03   369.6  749.32   379.3  748.59
   389.1  746.56   408.5  739.98   418.2  737.59     428  737.59   437.7  742.95
   457.2  760.19   496.1  784.23   505.8  792.01   525.2  809.83     535   817.9
   544.7  824.27   583.6  843.94   622.5  862.31     642  869.81   690.6  886.04
#Mann= 3 , 0 , 0
       0      .1       0   418.2    .045       0   437.7      .1       0
#XS Ineff= 2 , 0
          340.42  749.75
Permanent Ineff=
       F       F
Bank Sta=418.2,437.7
XS Rating Curve= 0 ,0
Exp/Cntr=0.3,0.1

Type RM Length L Ch R = 1 ,2220.2  ,195,193.3,190.5
XS GIS Cut Line= 3
     1479085.517      275287.127     1478742.635      275130.877
     1478397.583      274892.162
#Sta/Elev= 30
       0  852.93   173.9  763.03   193.2   754.3   202.9  751.43   222.2  747.09
   231.9  745.64   251.2  744.27   289.8  739.69   299.5  739.49   309.2  740.59
   328.5  745.67   338.2  747.11   445.1  746.76   454.9  745.15   474.4  736.72
   479.2735.8323   484.1  734.92   493.9  735.15   499.2736.1301   513.4  740.21
   523.2  744.58   552.4  761.13     572  771.28   620.8  792.91     650  806.65
   679.3     819   698.8  825.24   747.6  838.42   767.1  842.56   796.4  846.45
#Mann= 3 , 0 , 0
       0      .1       0   479.2    .045       0   499.2      .1       0
#XS Ineff= 2 , 0
          367.36  747.91
Permanent Ineff=
       F       F
Bank Sta=479.2,499.2
XS Rating Curve= 0 ,0
Exp/Cntr=0.3,0.1

Type RM Length L Ch R = 1 ,2027    ,318.4,320.8,323
XS GIS Cut Line= 2
     1479108.086      275127.593     1478431.003      274742.177
#Sta/Elev= 30
       0   826.3    19.5  816.09    58.4  793.98    97.4   774.9   126.6  761.96
   146.1  754.01   155.8  750.66   175.3  745.26     185  743.89   204.5  742.42
   233.7  738.11   243.5  737.48   253.2  738.21   272.7  744.06   282.4  745.39
   389.6  745.67   399.3  744.35   418.8  738.33   428.5  736.49   486.9  734.07
   496.7  733.86   506.4  734.74   516.2     739   525.9  745.96   535.6  751.56
   642.8  791.45   701.2  814.18   710.9  816.67   730.4  819.08   779.1  818.81
#Mann= 3 , 0 , 0
       0      .1       0   486.9    .045       0   506.4      .1       0
#XS Ineff= 2 , 0
          360.43  746.13
Permanent Ineff=
       F       F
Bank Sta=486.9,506.4
XS Rating Curve= 0 ,0
Exp/Cntr=0.3,0.1

Type RM Length L Ch R = 1 ,1706.1  ,308.4,310.9,312.8
XS GIS Cut Line= 2
     1479279.961      274917.524     1478599.406      274441.829
#Sta/Elev= 30
       0  832.86     127  771.54   195.4  744.34   205.1  741.27   214.9   739.9
   244.2  740.85     254  739.93   273.5  734.55   283.3  733.72   293.1  734.75
   322.4  742.41   332.1  743.79   410.3  744.97   439.6  744.93   449.4  744.13
   459.1  742.23   478.7  737.24   488.4  735.98   539.3732.1356     547  731.82
   556.8  733.04   559.3734.0374   566.6  736.95   586.1  748.54   644.7  780.38
   722.9   818.9   781.5  850.74     801  861.82   820.6  872.12   830.3  876.57
#Mann= 3 , 0 , 0
       0      .1       0   539.3    .045       0   559.3      .1       0
#XS Ineff= 2 , 0
          429.51  745.47
Permanent Ineff=
       F       F
Bank Sta=539.3,559.3
XS Rating Curve= 0 ,0
Exp/Cntr=0.3,0.1

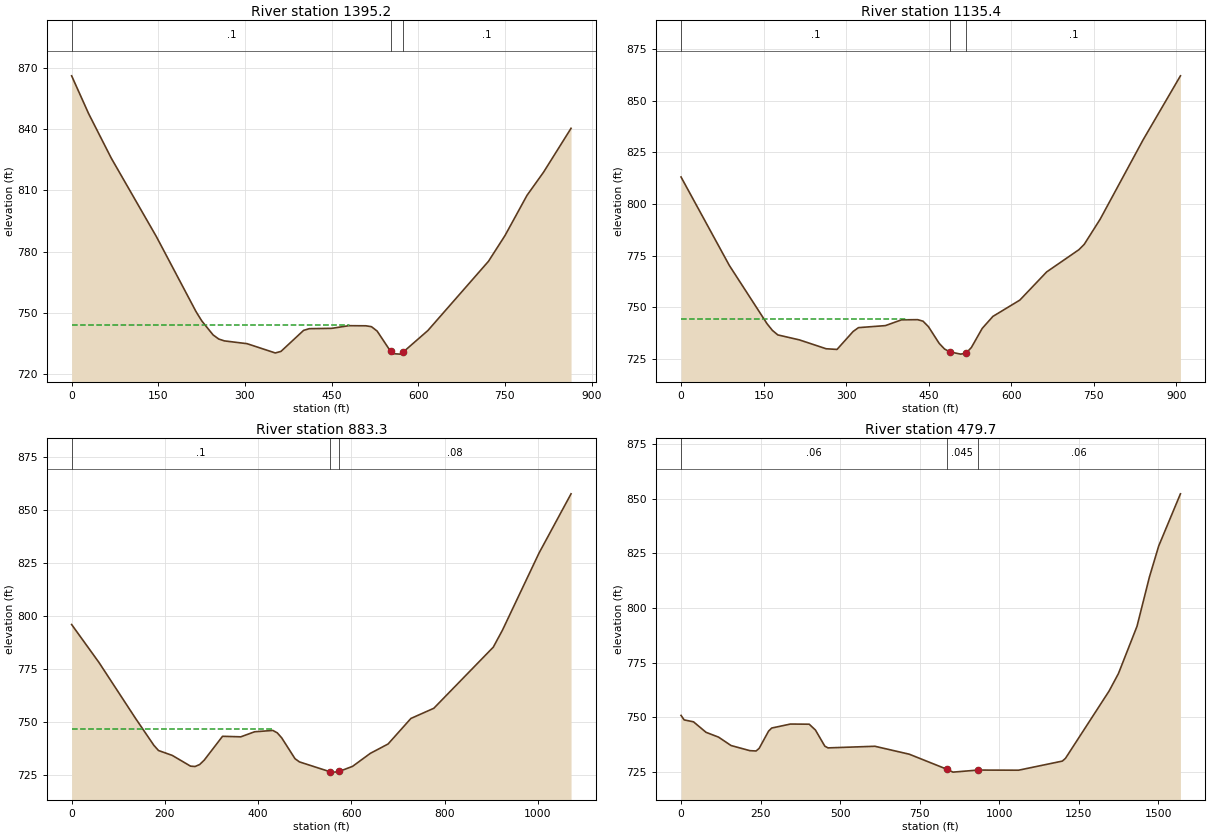
Type RM Length L Ch R = 1 ,1395.2  ,256.9,259.8,262.3
XS GIS Cut Line= 3
     1479463.555      274735.478     1478996.975      274347.023
     1478799.492      274182.093
#Sta/Elev= 30
       0  865.94    29.4  847.46    68.6   825.7   146.9  787.24   215.4  750.64
   225.2  746.17   244.8  739.31   254.6  737.29   264.4  736.38   303.6  735.02
   352.5  730.48   362.3  731.24   401.5  741.52   411.3  742.35   450.4  742.52
   479.8  743.81   509.2  743.76     519  743.31   528.8  741.17   548.4  732.82
   553.2731.4852   558.2   730.1     568  729.91   573.2730.7535   616.6  741.44
   721.5  775.29   750.1  787.88   788.2  807.53   816.8  818.84   864.4  840.29
#Mann= 3 , 0 , 0
       0      .1       0   553.2    .045       0   573.2      .1       0
#XS Ineff= 2 , 0
          479.75  744.26
Permanent Ineff=
       F       F
Bank Sta=553.2,573.2
XS Rating Curve= 0 ,0
Exp/Cntr=0.3,0.1

Type RM Length L Ch R = 1 ,1135.4  ,251.9,252.1,251.2
XS GIS Cut Line= 3
     1479509.128      274525.163     1479028.225      274025.163
     1478814.683      274016.482
#Sta/Elev= 30
       0  813.04    87.9   770.2   156.3  742.07   166.1  738.82   175.9  736.66
     215  734.26   263.8  729.96   283.4  729.64   312.7  738.32   322.4  740.18
   371.3  741.16   400.6  743.95   429.9  744.04   439.7   743.3   449.5  740.66
     469  732.59   478.8  729.83   488.6  728.45   508.1  727.37   517.9  727.85
   527.6  730.59   547.2  739.81   566.7  745.62   615.6   753.5   664.4  767.14
   722.9  777.87   732.6  780.47   761.7   792.7   839.4  830.93   907.4  861.96
#Mann= 3 , 0 , 0
       0      .1       0   488.6    .045       0   517.9      .1       0
#XS Ineff= 2 , 0
          410.54  744.55
Permanent Ineff=
       F       F
Bank Sta=488.6,517.9
XS Rating Curve= 0 ,0
Exp/Cntr=0.3,0.1

Type RM Length L Ch R = 1 ,883.3   ,419,403.6,386.6
XS GIS Cut Line= 4
     1479594.197      274415.166     1479381.524      274039.732
     1479207.912       273863.95     1478821.628      273933.395
#Sta/Elev= 30
       0  795.83    58.8  777.86   137.3  751.43   176.5  738.75   186.3  736.33
   215.7  734.04     255  728.95   264.8  728.79   274.6  729.72   284.4  731.81
   323.6  743.05   362.8   742.8   392.3  745.18   431.5  745.82     441  744.68
   450.5  742.31     479  732.48   488.5  730.96   553.2726.3704   564.5  726.13
     574  726.48   602.5  728.86   640.5  734.99   678.6  739.41   727.6  751.48
   776.7  756.28   904.2  785.14   923.8  793.12  1002.3  829.57    1071  857.55
#Mann= 3 , 0 , 0
       0      .1       0   553.2    .045       0     574     .08       0
#XS Ineff= 2 , 0
          431.11  746.63
Permanent Ineff=
       F       F
Bank Sta=553.2,574
XS Rating Curve= 0 ,0
Exp/Cntr=0.3,0.1

Type RM Length L Ch R = 1 ,479.7   ,475.1,479.7,481.8
XS GIS Cut Line= 4
     1479726.576      274232.874     1479696.194      273633.916
      1479006.09      273531.919     1478747.843      273620.895
#Sta/Elev= 30
       0  750.96     9.8   748.9    39.3  748.01    78.6  743.22     118  741.02
   157.3  737.18   216.3  734.84     236  734.68   245.8  735.91   275.3  743.76
   285.1  745.17   344.1     747   403.1  746.93   422.8  744.24   452.2  736.89
   462.1   736.1   609.6  736.84   717.6  733.22   835.5  726.37   855.2  725.02
   933.8  725.96  1061.5   725.9  1199.1  730.06  1208.9  731.31  1346.1  762.09
  1375.4  770.04  1433.9  791.68  1472.9  814.19  1502.2  828.42  1570.5  852.24
#Mann= 3 , 0 , 0
       0     .06       0   835.5    .045       0   933.8     .06       0
Bank Sta=835.5,933.8
XS Rating Curve= 0 ,0
Exp/Cntr=0.3,0.1

Chan Stop Cuts=-1
Use User Specified Reach Order=0
Composite Channel Slope=5